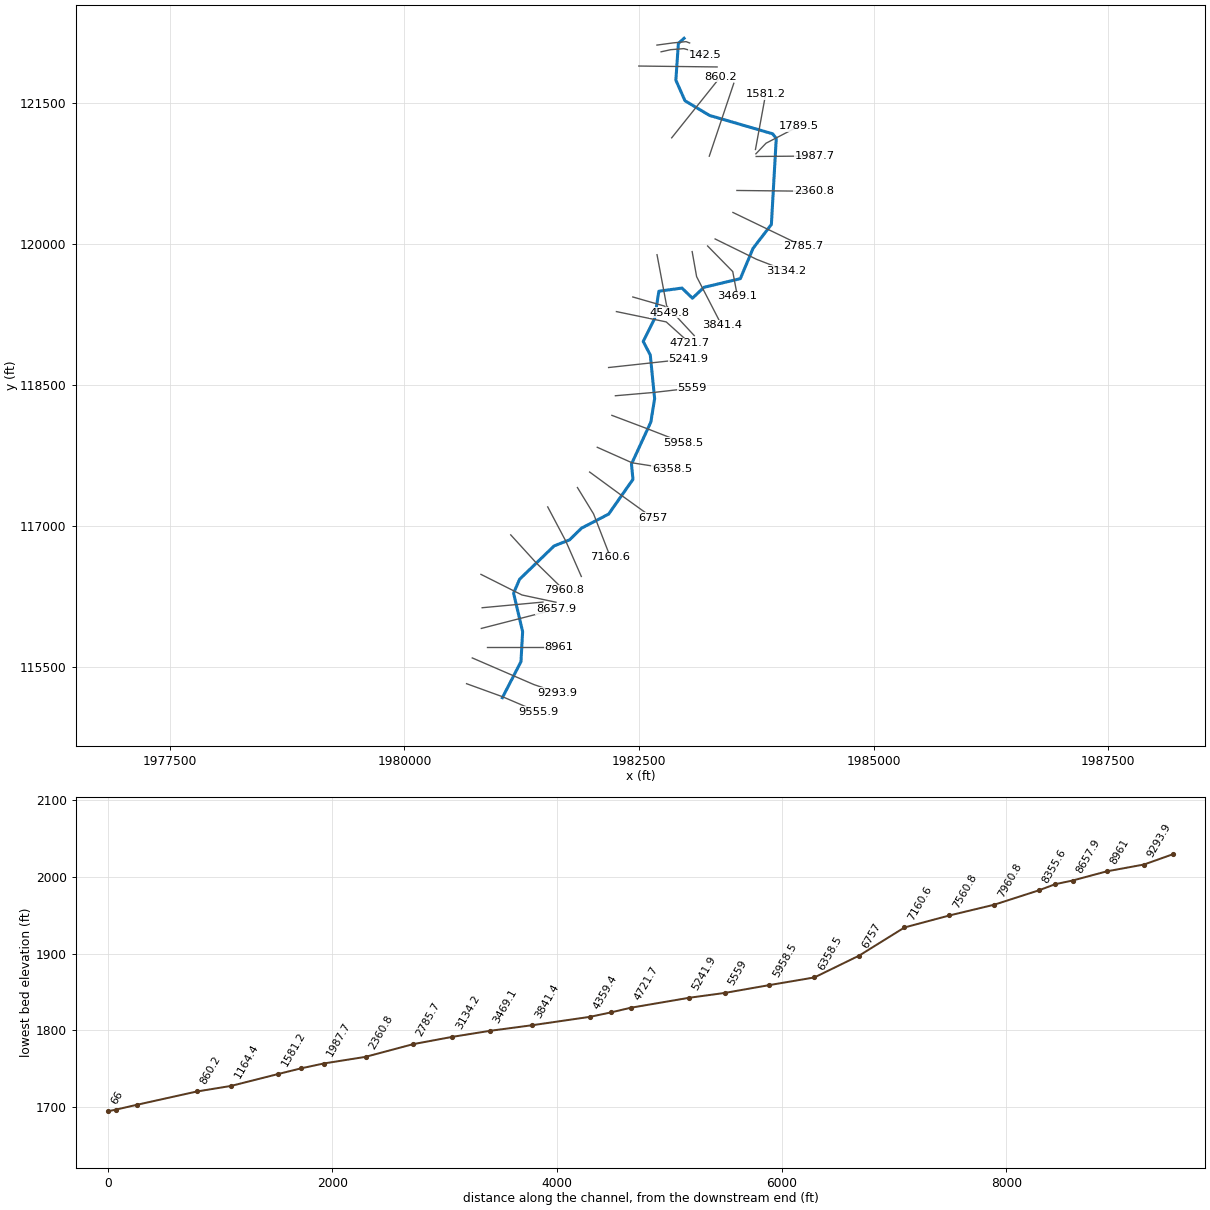
--- PgnCrk.prj (project) ---

Proj Title=PgnCrk
Current Plan=p01
Default Exp/Contr=0,0
English Units
Geom File=g01
Flow File=f01
Plan File=p01
BEGIN DESCRIPTION:
END DESCRIPTION:
DSS Export Rating Curves= 0
DSS Export Rating Curve Sorted= 0
DSS Export Volume Flow Curves= 0
DXF OffsetX= 0
DXF OffsetY= 0
DXF ScaleX= 0
DXF ScaleY= 0

--- PgnCrk.p01 (plan) ---

Plan Title=Floodplain
Program Version=4.00
Geom File=g01
Flow File=f01
K Sum by GR=0
Std Step Tol=0.01
Critical Tol=0.01
Num of Std Step Trials=20
Max Error Tol=0.3
Flow Tol Ratio=0.001
Split Flow NTrial=30
Split Flow Tol=0.02
Split Flow Ratio=0.02
Log Output Level=0
Friction Slope Method=1
Unsteady Friction Slope Method=2
Unsteady Bridges Friction Slope Method=1
Global Log Level=0
CheckData=False
Run HTab=0
Run UNet=0
Run PostProcess=0
UNET Theta=0
UNET Theta Warmup=0
UNET ZTol=0
UNET ZSATol=0
UNET MxIter=0
UNET MaxInSteps=0
UNET DtIC=0
UNET DtMin=0
UNET MaxCRTS=0
UNET WFStab=0
UNET SFStab=0
UNET WFX=0
UNET SFX=0
UNET DSS MLevel=0
UNET DZMax Abort=0
UNET Convert EG Bridges=0
UNET Use Existing IB Tables=0
UNET Froude Limit=0
UNET Froude Power=0
Write IC File=0
Echo Input=False
Echo Output=False
Write Detailed=0

--- PgnCrk.f01 (steady flow) ---

Flow Title=NFF Regression Equation
Program Version=4.00
Number of Profiles=1
Profile Names=P100yr
River Rch & RM=PgnCrk,Main      ,9555.9
510.8924
River Rch & RM=PgnCrk,Main      ,7160.6
537.6899
River Rch & RM=PgnCrk,Main      ,6757
788.7079
River Rch & RM=PgnCrk,Main      ,5958.5
853.2057
River Rch & RM=PgnCrk,Main      ,3469.1
941.5183
River Rch & RM=PgnCrk,Main      ,1987.7
1045.187
River Rch & RM=PgnCrk,Main      ,330.6
1153.118
Boundary for River Rch & Prof#=PgnCrk,Main      ,1
Up Type=0
Dn Type=3
Dn Slope=0.031703

--- PgnCrk.g01 (geometry) ---

Geom Title=USGS 3m DEM
Program Version=4.10

River Reach=PgnCrk          ,Main
Reach XY= 30
     1981044.346      115170.805     1981242.246      115554.372
     1981260.159      115873.588     1981163.805      116283.745
     1981227.607      116432.182     1981596.097      116787.651
     1981760.159      116851.453     1981887.763      116976.453
     1982176.826      117126.193     1982435.941      117495.984
     1982419.984      117658.977     1982626.765       118106.98
     1982666.992      118355.711     1982620.836      118820.203
     1982545.315      118964.734     1982666.409      119208.224
     1982711.982      119499.891     1982958.076      119533.745
     1983070.055      119425.672     1983192.451      119541.557
     1983580.472      119634.005     1983715.888      119956.922
     1983911.201      120210.828     1983963.176      121127.853
     1983923.778      121177.109     1983252.347      121372.286
     1982990.628      121528.536     1982893.098      121748.179
      1982920.06      122139.409     1982980.902      122194.363

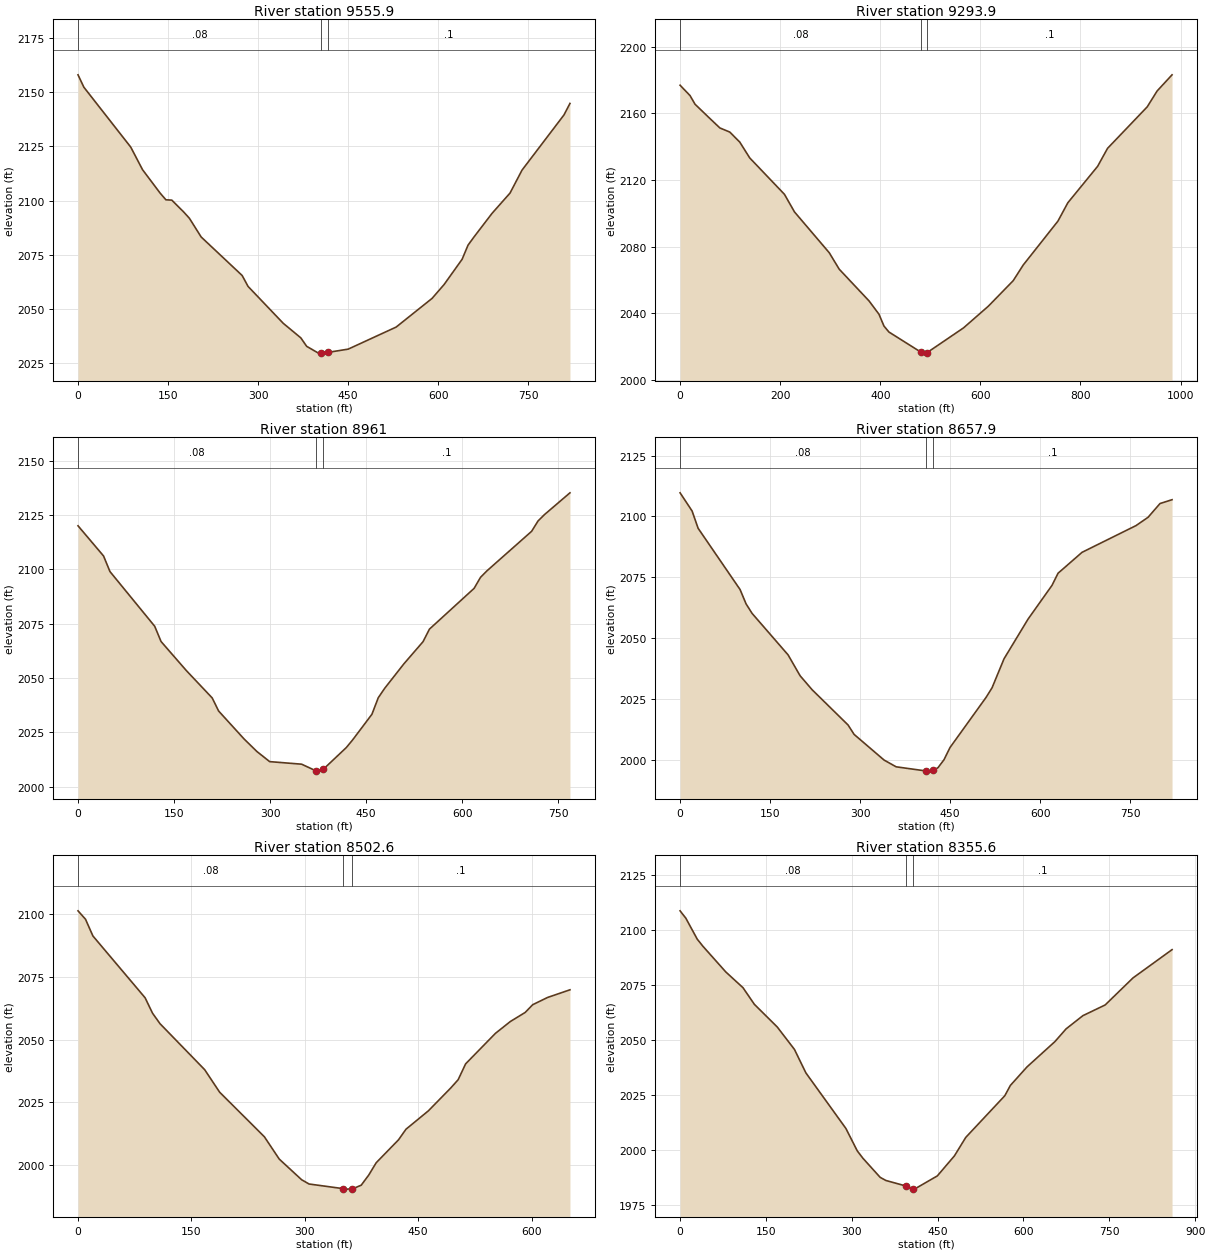
Type RM Length L Ch R = 1 ,9555.9  ,261.6,261.8,261.6
XS GIS Cut Line= 3
     1980662.509      115319.772     1981048.285      115179.997
     1981424.542      115018.742
#Sta/Elev= 30
       0 2157.94     9.8 2152.22    87.9 2124.64   107.5 2114.26   136.8 2103.48
   146.5 2100.38   156.3 2100.23   175.8 2094.86   185.6 2091.88   205.2 2083.26
   273.5 2065.52   283.3 2060.51   341.9 2043.52   371.2 2036.81     381  2032.9
   400.6 2029.77   404.3  2029.8   416.3  2030.1   450.2 2031.61   530.1 2041.77
     590 2054.99     610 2061.37     640 2072.99   649.9 2079.52   659.9  2083.3
   689.9 2094.15   719.8 2103.47   739.8 2114.04   809.7 2139.46   819.7 2144.76
#Mann= 3 , 0 , 0
       0     .08       0   404.3    .045       0   416.3      .1       0
Bank Sta=404.3,416.3
XS Rating Curve= 0 ,0
Exp/Cntr=0.3,0.1

Type RM Length L Ch R = 1 ,9293.9  ,325.6,332.7,341.3
XS GIS Cut Line= 3
     1980723.522      115594.091     1981380.194      115310.329
     1981633.822      115224.949
#Sta/Elev= 30
       0 2176.93    19.9  2170.7    29.8 2165.54    59.6 2156.94    79.5 2151.28
    99.4 2148.79   119.2 2142.81   139.1 2133.31   208.6 2111.41   228.5  2100.9
   298.1 2076.35   317.9 2066.51   377.6 2047.43   397.4 2039.45   407.4 2032.34
   417.3 2028.77   481.6 2016.61   486.8  2016.1   493.6 2016.41   566.3 2031.24
     616 2044.29   665.7 2059.62   685.6 2068.98     755 2095.35   774.8 2106.37
   834.3 2128.24   854.1 2139.02   933.4 2163.94   953.2 2173.48     983 2183.17
#Mann= 3 , 0 , 0
       0     .08       0   481.6    .045       0   493.6      .1       0
Bank Sta=481.6,493.6
XS Rating Curve= 0 ,0
Exp/Cntr=0.3,0.1

Type RM Length L Ch R = 1 ,8961    ,297.9,303.2,308.5
XS GIS Cut Line= 2
     1980879.215      115714.627     1981647.633      115714.627
#Sta/Elev= 30
       0 2120.04    39.9 2106.16    49.9 2098.99   119.8 2073.82   129.7  2066.8
   169.6  2053.3   209.6 2040.84   219.6 2034.84   259.5 2021.93   279.4  2016.2
   299.4 2011.54   349.3 2010.36     371 2007.39   379.2 2007.17     383 2007.99
   419.1 2018.02   429.1 2021.59   459.1 2033.34     469 2040.94     479 2045.27
     509 2056.53   538.9 2066.72   548.9 2072.49   618.7 2091.26   628.7 2096.33
   638.7 2099.31   708.5  2117.5   718.5 2122.24   728.5 2125.17   768.4 2135.21
#Mann= 3 , 0 , 0
       0     .08       0     371    .045       0     383      .1       0
Bank Sta=371,383
XS Rating Curve= 0 ,0
Exp/Cntr=0.3,0.1

Type RM Length L Ch R = 1 ,8657.9  ,158.6,155.3,151.9
XS GIS Cut Line= 2
     1980819.997      115908.379     1981614.143       116112.22
#Sta/Elev= 30
       0 2109.66      20 2102.19      30  2095.1     100 2069.88     110 2063.98
     120 2060.08     180 2043.02     200 2034.44     220  2028.7     280 2014.18
     290 2010.33     340 1999.77     360    1997   410.2 1995.27   419.9 1995.22
   422.2 1995.55   429.9 1996.65   439.9 1999.93   449.9 2004.94   509.9 2025.52
   519.9 2029.47   539.9 2041.42   579.9 2057.72   619.9 2071.63   629.9 2076.59
   669.9 2085.19   759.9 2096.19   779.9 2099.59   799.9 2105.26   819.9 2106.83
#Mann= 3 , 0 , 0
       0     .08       0   410.2    .045       0   422.2      .1       0
Bank Sta=410.2,422.2
XS Rating Curve= 0 ,0
Exp/Cntr=0.3,0.1

Type RM Length L Ch R = 1 ,8502.6  ,159,147,135
XS GIS Cut Line= 2
     1980828.834      116128.814     1981476.717      116189.082
#Sta/Elev= 30
       0 2101.39     9.9 2098.05    19.7 2091.37    88.7 2066.74    98.6 2060.56
   108.4 2056.41   167.6 2038.03   187.3 2029.09   246.5 2011.31   266.2  2002.4
   295.8 1994.17   305.6 1992.47   350.8 1990.62   354.9 1990.43   362.8  1990.5
   374.6    1992   384.5 1996.02   394.4 2000.95   423.9 2010.08   433.8 2014.31
   463.4 2021.64   492.9 2030.72   502.8 2034.05   512.7 2040.38   552.1 2052.53
   571.8 2057.25   591.5 2060.88   601.4 2063.96   621.1 2066.85   650.7  2069.9
#Mann= 3 , 0 , 0
       0     .08       0   350.8    .045       0   362.8      .1       0
Bank Sta=350.8,362.8
XS Rating Curve= 0 ,0
Exp/Cntr=0.3,0.1

Type RM Length L Ch R = 1 ,8355.6  ,403.2,394.8,387.6
XS GIS Cut Line= 3
     1980815.983      116484.193     1981253.379      116264.574
     1981615.439      116187.436
#Sta/Elev= 30
       0 2108.56      10 2105.23      30  2095.7      40 2092.46    79.9 2080.83
   109.9  2073.7   129.8 2066.15   169.8 2055.87   199.8 2045.71   219.8 2035.06
   289.7 2009.86   309.6 1999.68   319.6  1996.3   349.6 1987.68   359.6 1986.26
   395.1 1983.72   407.1  1982.5   409.5 1982.34   449.5 1988.34   479.4 1997.44
   499.2 2005.81   567.4  2024.7   577.1 2029.37   606.3  2037.8     655 2049.26
   674.5 2055.03   703.8 2061.01   742.7 2065.86   791.4 2078.13   859.6 2090.95
#Mann= 3 , 0 , 0
       0     .08       0   395.1    .045       0   407.1      .1       0
Bank Sta=395.1,407.1
XS Rating Curve= 0 ,0
Exp/Cntr=0.3,0.1

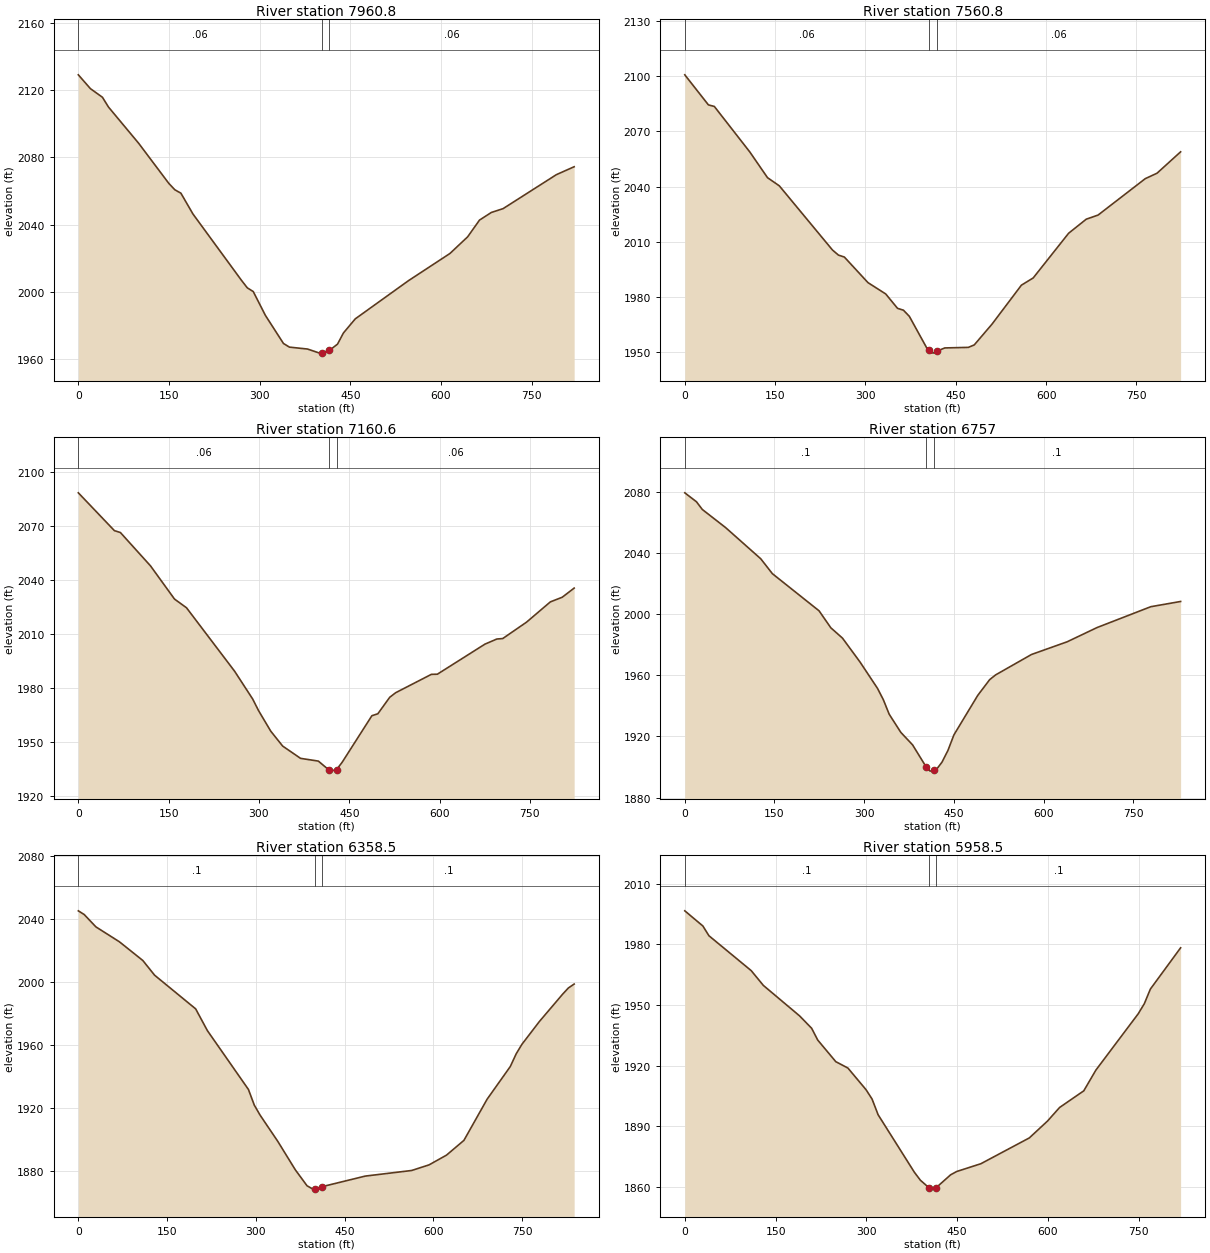
Type RM Length L Ch R = 1 ,7960.8  ,405.7,399.9,391.5
XS GIS Cut Line= 3
     1981133.283      116904.972     1981408.892      116602.474
     1981702.865      116315.157
#Sta/Elev= 30
       0 2128.99      20 2120.78    39.9 2115.65    49.9 2109.85    99.8 2088.34
   149.7 2064.51   159.7 2060.71   169.7 2058.69   189.6 2046.35   269.5 2007.13
   279.5 2002.49   289.4 2000.26   309.4 1986.17   339.4 1969.42   349.3 1967.26
   379.3 1966.12   399.2  1963.7   403.2 1963.92   415.2 1965.29   428.8 1969.04
   438.6 1975.68   458.2 1984.06   546.2 2006.73   614.8 2022.88   644.1 2032.77
   663.7 2042.71   683.3 2047.24   702.8 2049.53   790.9  2069.7   820.3  2074.4
#Mann= 3 , 0 , 0
       0     .06       0   403.2    .045       0   415.2     .06       0
Bank Sta=403.2,415.2
XS Rating Curve= 0 ,0
Exp/Cntr=0.3,0.1

Type RM Length L Ch R = 1 ,7560.8  ,402.5,400.1,399.1
XS GIS Cut Line= 3
     1981527.489      117202.802     1981720.253      116838.484
      1981885.58      116461.948
#Sta/Elev= 30
       0 2100.71    39.2  2084.4    49.1 2083.53     108 2058.83   137.4 2044.87
     157 2040.44   245.3 2005.59   255.2 2002.85     265 2001.79   304.2 1987.91
   333.7 1981.75   353.3 1973.95   363.1 1972.95   372.9 1969.61   402.4  1952.1
   406.2 1951.15   412.2 1949.64   418.2 1950.65   431.8 1952.46   470.9 1952.76
   480.7  1954.1   510.1 1965.34     559 1986.53   578.6 1990.46   637.4 2014.71
   666.7 2022.35   686.3 2024.58   764.7 2044.35   784.2  2047.3   823.4 2058.91
#Mann= 3 , 0 , 0
       0     .06       0   406.2    .045       0   418.2     .06       0
Bank Sta=406.2,418.2
XS Rating Curve= 0 ,0
Exp/Cntr=0.3,0.1

Type RM Length L Ch R = 1 ,7160.6  ,390.8,403.1,415.7
XS GIS Cut Line= 3
     1981844.333      117408.941     1982016.305      117127.946
     1982195.285      116667.564
#Sta/Elev= 30
       0 2088.48    59.9 2067.49    69.9 2066.43   119.8 2047.95   159.7 2029.51
   179.7 2024.65   259.6 1989.41   289.5 1974.03   299.5 1967.46   319.5 1956.19
   339.3  1947.9     369 1941.07   398.6 1939.55   416.9 1934.41   418.4 1933.98
   428.9 1934.84   438.1 1938.88   487.5 1964.74   497.4 1965.82   517.1 1974.96
     527 1977.51   586.3 1987.71   596.2 1987.78   675.2 2004.47     695 2007.32
   704.8 2007.58   744.4  2016.7   783.9 2027.94   803.6 2030.51   823.4 2035.59
#Mann= 3 , 0 , 0
       0     .06       0   416.9    .045       0   428.9     .06       0
Bank Sta=416.9,428.9
XS Rating Curve= 0 ,0
Exp/Cntr=0.3,0.1

Type RM Length L Ch R = 1 ,6757    ,393.8,398.5,408.7
XS GIS Cut Line= 3
     1981974.191      117574.252     1982305.073      117331.859
     1982645.144      117087.088
#Sta/Elev= 30
       0 2079.65    19.5  2073.8    29.3 2068.74    68.4 2056.82     127 2036.44
   146.5 2026.67   224.6 2002.32   244.2 1991.22   263.7 1984.45     293 1968.82
   322.3 1951.52     332 1944.13   341.8  1934.6   361.3 1922.68   380.9 1914.53
   404.2 1899.69   410.2  1897.3   416.2 1897.73   420.1 1898.01   430.1 1903.16
   440.1 1910.88   450.1 1921.07     490 1946.97   509.9 1957.26   519.9 1960.37
   579.8 1973.72   639.6 1982.07   689.5 1991.38   779.3 2005.03   829.2 2008.46
#Mann= 3 , 0 , 0
       0      .1       0   404.2    .045       0   416.2      .1       0
Bank Sta=404.2,416.2
XS Rating Curve= 0 ,0
Exp/Cntr=0.3,0.1

Type RM Length L Ch R = 1 ,6358.5  ,398.8,400,395.2
XS GIS Cut Line= 3
     1982055.632      117837.639        1982427.      117672.424
     1982853.338      117605.435
#Sta/Elev= 30
       0 2045.31     9.9 2042.97    29.7 2035.14    69.4 2025.68     109 2013.81
   128.9 2004.49   198.3 1983.14   218.1 1969.35   287.5 1932.03   297.4  1922.1
   307.3 1915.69   337.1 1899.12   366.8 1881.03   386.6 1870.92   396.6 1868.82
   400.5 1869.14   412.5 1870.43   484.9 1877.08   563.4 1880.64   592.8 1884.21
   622.2 1890.36   651.7 1899.74   690.9 1925.85   730.1 1946.58     740 1954.61
   749.8  1960.7   779.2  1975.1   818.4  1992.4   828.2 1996.37     838 1998.88
#Mann= 3 , 0 , 0
       0      .1       0   400.5    .045       0   412.5      .1       0
Bank Sta=400.5,412.5
XS Rating Curve= 0 ,0
Exp/Cntr=0.3,0.1

Type RM Length L Ch R = 1 ,5958.5  ,389.9,399.3,409.6
XS GIS Cut Line= 3
     1982211.375      118177.903     1982594.236      118033.411
     1982976.358      117884.898
#Sta/Elev= 30
       0 1996.65    29.9 1989.13    39.9 1984.31   109.8 1967.02   129.8 1959.72
   189.6 1944.65   209.6 1938.49   219.6 1932.68   249.5 1921.96   269.5 1918.81
   299.4 1908.11   309.4 1903.46   319.4 1895.69   379.3 1867.22   389.3 1863.25
   403.2 1859.61   409.2 1858.86   415.2 1859.55   439.2 1865.95   449.2 1867.58
   489.2 1871.44   569.2 1884.21   599.2 1892.54   619.2 1899.27   659.2 1907.53
   679.2 1917.79   749.2  1945.7   759.2 1950.65   769.2 1957.89   819.2 1978.34
#Mann= 3 , 0 , 0
       0      .1       0   403.2    .045       0   415.2      .1       0
Bank Sta=403.2,415.2
XS Rating Curve= 0 ,0
Exp/Cntr=0.3,0.1

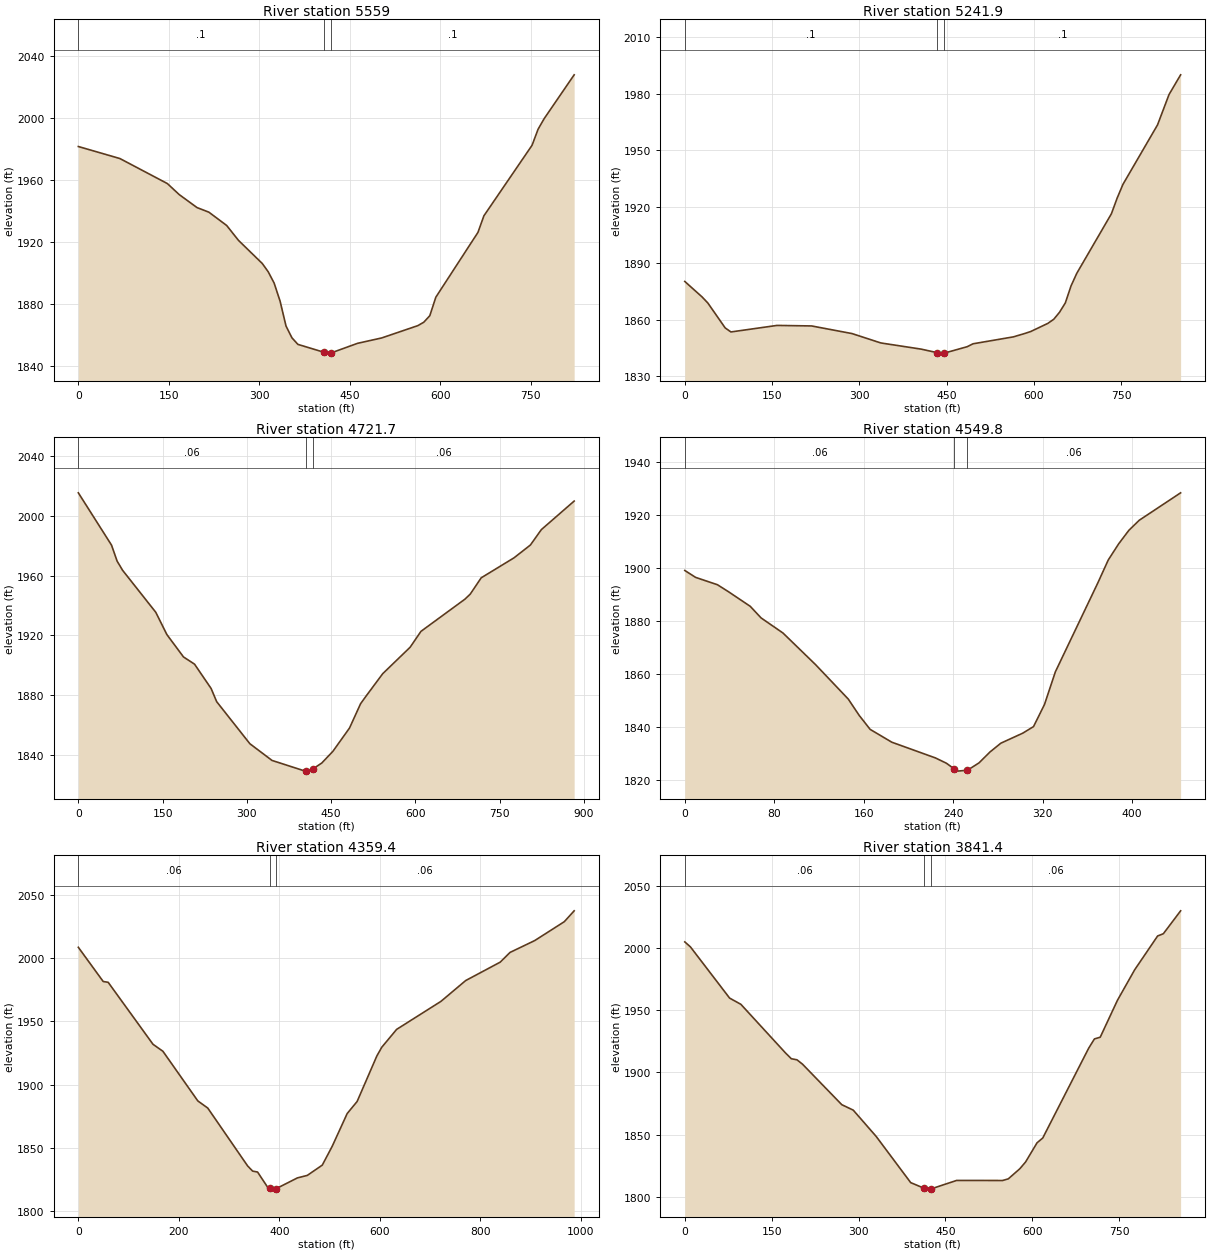
Type RM Length L Ch R = 1 ,5559    ,316.7,317.1,317
XS GIS Cut Line= 3
      1982248.85      118386.724     1982660.495      118422.149
     1983066.682      118468.761
#Sta/Elev= 30
       0 1981.89    68.9 1974.13   147.6 1957.98   167.2 1950.89   196.8 1942.48
   216.4 1939.53   245.9 1930.95   265.6  1921.3     305  1906.4   314.8 1901.07
   324.6 1893.78   334.5 1882.09   344.3 1866.08   354.1 1858.48     364 1854.23
   407.2 1849.13   413.2 1848.58   419.2 1848.73     463 1854.91   502.9 1858.37
   562.8 1866.31   572.7 1868.51   582.7 1872.74   592.7 1884.68   662.5 1926.47
   672.4  1937.2   752.2 1982.68   762.2 1993.04   772.2 1999.82     822 2028.14
#Mann= 3 , 0 , 0
       0      .1       0   407.2    .045       0   419.2      .1       0
Bank Sta=407.2,419.2
XS Rating Curve= 0 ,0
Exp/Cntr=0.3,0.1

Type RM Length L Ch R = 1 ,5241.9  ,526.4,520.1,513.8
XS GIS Cut Line= 2
     1982176.392      118687.384     1983023.564      118779.396
#Sta/Elev= 30
       0 1880.34    29.7 1872.12    39.6  1868.9    69.4 1855.66    79.3 1853.51
   158.5 1856.98     218  1856.7   287.4 1852.65   336.9 1847.67   406.3 1844.38
   434.1 1842.49   445.9 1842.26   446.1 1842.27   485.5 1845.69   495.4 1847.22
   564.8  1850.9   584.6 1852.72   594.5 1853.73   624.2  1858.1   634.2 1860.27
   644.1 1863.99     654 1868.92   663.9 1878.01   673.8 1884.71   733.2 1916.29
   743.2  1924.7   753.1 1931.95   812.5 1963.52   832.3 1979.67   852.2 1990.13
#Mann= 3 , 0 , 0
       0      .1       0   434.1    .045       0   446.1      .1       0
Bank Sta=434.1,446.1
XS Rating Curve= 0 ,0
Exp/Cntr=0.3,0.1

Type RM Length L Ch R = 1 ,4721.7  ,173.5,171.9,170.3
XS GIS Cut Line= 3
     1982259.738      119283.069     1982790.374      119173.296
     1983043.849      118945.386
#Sta/Elev= 30
       0  2015.4    59.1 1980.42      69 1969.77    78.8 1963.59   137.9 1935.48
   157.6 1920.61   187.2 1905.63   206.9 1900.78   236.4 1884.51   246.3 1875.69
   305.4 1847.57   344.8  1836.4   403.9 1829.24   405.5 1829.34   417.5 1830.69
   433.5 1834.69   453.2 1842.49   482.8 1858.08   502.5 1874.34   512.3 1879.45
   541.9 1894.42   590.6 1912.07     610 1922.74     688 1944.19   697.7 1947.64
   717.2 1958.54   775.6  1971.9   804.8 1980.49   824.3 1990.79   882.7 2009.88
#Mann= 3 , 0 , 0
       0     .06       0   405.5    .045       0   417.5     .06       0
Bank Sta=405.5,417.5
XS Rating Curve= 0 ,0
Exp/Cntr=0.3,0.1

Type RM Length L Ch R = 1 ,4549.8  ,214.2,190.2,166.3
XS GIS Cut Line= 3
     1982434.415      119438.853      1982771.54      119341.859
     1982828.983      119269.348
#Sta/Elev= 30
       0    1899     9.7 1896.39    29.2 1893.62      39    1891    58.5 1885.48
    68.2  1881.1    87.7 1875.43   116.9 1863.48   146.2 1850.46   155.9 1844.33
   165.7 1839.05   185.1  1834.2   224.1 1828.27   233.9 1826.27   240.7 1824.18
   243.6 1823.29   252.7 1823.62   263.1 1826.42   272.8 1830.49   282.6 1833.84
   302.1  1837.6   311.8  1840.1   321.6 1848.45   331.3 1860.75   369.3 1894.33
   378.6 1902.96   387.8 1908.98     397 1914.14   406.3 1917.95   443.3  1928.3
#Mann= 3 , 0 , 0
       0     .06       0   240.7    .045       0   252.7     .06       0
Bank Sta=240.7,252.7
XS Rating Curve= 0 ,0
Exp/Cntr=0.3,0.1

Type RM Length L Ch R = 1 ,4359.4  ,511.6,518,524.1
XS GIS Cut Line= 3
     1982692.438       119888.98     1982795.082      119343.742
     1983089.119      119027.356
#Sta/Elev= 30
       0 2008.37    49.5 1981.36    59.4 1980.73   148.6 1931.79   168.4 1926.24
   237.8 1887.07   257.6 1881.42   336.8  1835.8   346.8 1831.67   356.7 1830.91
   376.5 1819.05   380.8 1818.34   386.4 1817.42   392.8 1817.61   435.9 1826.27
   455.7 1828.27   485.5 1836.39   505.3  1851.3     535 1877.09   554.8 1886.62
   594.1  1922.6   603.9 1929.49   633.4 1943.54   721.7  1965.7   770.8  1982.1
   839.5 1996.63   859.1 2004.32   908.2 2013.67   967.1 2028.59   986.7 2037.17
#Mann= 3 , 0 , 0
       0     .06       0   380.8    .045       0   392.8     .06       0
Bank Sta=380.8,392.8
XS Rating Curve= 0 ,0
Exp/Cntr=0.3,0.1

Type RM Length L Ch R = 1 ,3841.4  ,377.4,372,366.5
XS GIS Cut Line= 3
     1983066.899       119922.23     1983114.315      119655.441
     1983382.696      119135.629
#Sta/Elev= 30
       0 2004.82     9.7 2000.82    77.4  1959.7    96.8 1954.73   174.2 1915.52
   183.9 1911.05   193.6 1910.19   203.2 1906.69     271 1874.18   290.8  1869.8
   330.5 1848.64     390 1811.62   412.8 1807.17   419.7  1806.4   424.8 1806.52
   469.3 1813.38   548.6 1813.32   558.5 1814.64   578.4 1822.76   588.3 1828.16
   608.1 1843.56     618 1847.44   697.3 1919.53   707.2 1926.94   717.2 1928.33
   746.9 1957.91   776.6 1982.38   816.3 2009.56   826.2 2011.39     856 2029.75
#Mann= 3 , 0 , 0
       0     .06       0   412.8    .045       0   424.8     .06       0
Bank Sta=412.8,424.8
XS Rating Curve= 0 ,0
Exp/Cntr=0.3,0.1

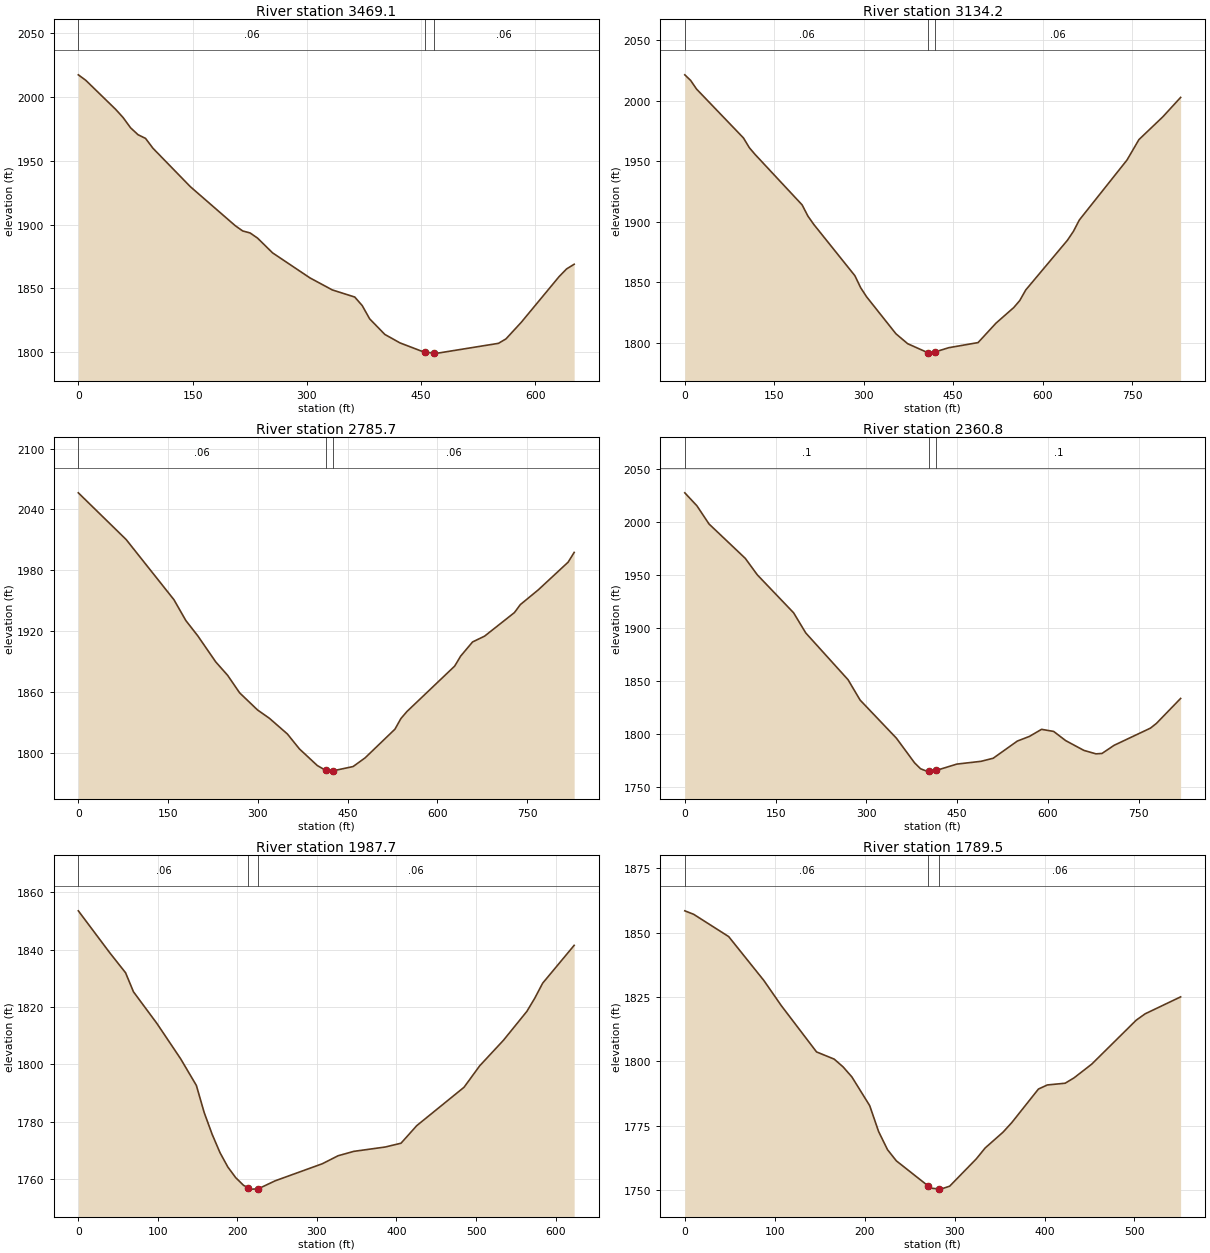
Type RM Length L Ch R = 1 ,3469.1  ,314.8,334.9,355.1
XS GIS Cut Line= 3
     1983231.539      119981.982     1983499.466      119709.117
     1983549.375      119445.444
#Sta/Elev= 30
       0  2017.5     9.8 2013.19      49 1990.41    58.8 1983.96    68.6 1975.92
    78.4 1970.51    88.2 1967.64      98 1959.87   147.1 1929.71   205.9 1899.18
   215.7 1895.03   225.5 1893.44   235.3 1889.38   254.9 1877.85     304  1858.2
   333.4 1848.74   362.8 1843.18   372.6 1836.48   382.4 1826.05   402.3 1813.84
   422.2 1807.19   454.6 1799.79   466.6 1799.38   471.9 1799.17   551.4 1806.84
   561.3 1810.33   581.2 1823.23   630.9  1859.1   640.8  1865.2   650.8 1868.89
#Mann= 3 , 0 , 0
       0     .06       0   454.6    .045       0   466.6     .06       0
Bank Sta=454.6,466.6
XS Rating Curve= 0 ,0
Exp/Cntr=0.3,0.1

Type RM Length L Ch R = 1 ,3134.2  ,348.2,348.4,348.6
XS GIS Cut Line= 3
     1983311.491      120056.877      1983752.78      119840.012
     1984069.455       119717.29
#Sta/Elev= 30
       0 2021.35     9.8 2016.72    19.7 2009.58    98.3  1969.2   108.2 1961.13
     118 1955.46   196.7 1913.86   206.5 1904.53   216.4 1897.62   285.2 1855.29
     295 1845.28   304.8 1837.87     354 1807.31   373.7  1799.1   407.8  1791.6
     413 1791.32   419.8 1792.32   442.5  1795.8   491.7 1800.03   521.7 1816.07
   551.6 1829.02   561.6 1834.78   571.6  1843.5   641.5  1884.6   651.5  1891.9
   661.5 1901.37   741.4 1950.93   761.4 1967.81   801.4 1986.61   831.3 2002.68
#Mann= 3 , 0 , 0
       0     .06       0   407.8    .045       0   419.8     .06       0
Bank Sta=407.8,419.8
XS Rating Curve= 0 ,0
Exp/Cntr=0.3,0.1

Type RM Length L Ch R = 1 ,2785.7  ,415.4,424.9,434.4
XS GIS Cut Line= 2
     1983501.506      120339.015     1984248.154      119979.293
#Sta/Elev= 30
       0 2056.38    79.9 2010.32   159.8 1950.95   179.7 1930.39   199.7 1915.26
   229.7 1889.56   249.6 1876.31   269.6 1859.06   299.6 1842.14   319.5 1833.88
   349.5 1818.45   369.5 1803.77   399.4 1787.36   413.6  1782.5   419.4 1781.81
   425.6 1782.08   459.3 1786.33   479.3 1794.87   529.2 1823.17   539.2 1833.68
   549.2 1840.57   629.1 1885.44   639.1 1895.31     659 1909.26     679 1914.95
   728.9  1938.2   738.9 1946.13   768.9 1960.68   818.8 1988.01   828.8 1997.57
#Mann= 3 , 0 , 0
       0     .06       0   413.6    .045       0   425.6     .06       0
Bank Sta=413.6,425.6
XS Rating Curve= 0 ,0
Exp/Cntr=0.3,0.1

Type RM Length L Ch R = 1 ,2360.8  ,372,373.1,374.1
XS GIS Cut Line= 3
     1983543.866      120573.203     1983953.342        120568.8
     1984362.819      120564.398
#Sta/Elev= 30
       0 2027.68      20 2015.47      40 1998.31    99.9 1965.88   119.8 1950.32
   179.8 1914.49   199.8 1895.54   269.7 1851.39   289.6 1832.22   349.6 1796.25
   379.5 1773.04   389.5 1767.41   399.5 1765.21   403.5 1765.23   415.5  1765.9
   449.4 1771.85   489.4 1774.46   509.4 1777.36   549.3 1793.56   569.3 1797.97
   589.3 1804.62   609.3 1802.65   629.2 1793.96   659.2 1784.77   679.2  1781.5
   689.2  1781.9   709.1 1789.55   769.1 1805.74     779  1810.2     819 1833.77
#Mann= 3 , 0 , 0
       0      .1       0   403.5    .045       0   415.5      .1       0
Bank Sta=403.5,415.5
XS Rating Curve= 0 ,0
Exp/Cntr=0.3,0.1

Type RM Length L Ch R = 1 ,1987.7  ,188.9,198.2,207.4
XS GIS Cut Line= 2
     1983749.014      120935.197     1984372.398       120940.22
#Sta/Elev= 30
       0 1853.54    39.6 1838.89    59.4 1831.95    69.3 1825.33      99 1814.21
   128.6 1801.98   148.4 1792.69   158.3 1783.18   168.2 1775.68   178.1 1769.26
     188 1764.24   197.9 1760.53   207.8 1757.84   213.9 1757.04   217.7 1756.54
   225.9 1756.61   247.4 1759.43   306.8 1765.39   326.6 1768.17   346.3  1769.7
   385.9 1771.22   405.7 1772.54   425.5 1778.67   484.9 1792.03   504.7 1799.54
   534.4 1808.39     564 1818.51   573.9  1823.1   583.8 1828.32   623.4 1841.51
#Mann= 3 , 0 , 0
       0     .06       0   213.9    .045       0   225.9     .06       0
Bank Sta=213.9,225.9
XS Rating Curve= 0 ,0
Exp/Cntr=0.3,0.1

Type RM Length L Ch R = 1 ,1789.5  ,188.8,208.3,227.8
XS GIS Cut Line= 3
     1983746.189      120963.448     1983854.001      121076.505
     1984204.791      121258.197
#Sta/Elev= 30
       0 1858.45     9.8 1857.11    48.8 1848.44    87.9 1831.39   107.4 1821.57
   146.5 1803.63   166.1 1800.84     176 1797.82   185.8 1793.91   205.6 1782.76
   215.5  1772.7   225.4 1765.66   235.2 1761.32   270.3 1751.65   274.7 1750.67
   282.3 1750.41   284.6 1750.33   294.5 1751.47   324.1 1762.08     334 1766.33
   353.8 1772.44   363.6 1776.19   393.2 1789.21   403.1  1790.8   422.9 1791.47
   432.8 1793.56   452.5  1798.9   501.9 1815.96   511.8 1818.43   551.3 1825.02
#Mann= 3 , 0 , 0
       0     .06       0   270.3    .045       0   282.3     .06       0
Bank Sta=270.3,282.3
XS Rating Curve= 0 ,0
Exp/Cntr=0.3,0.1

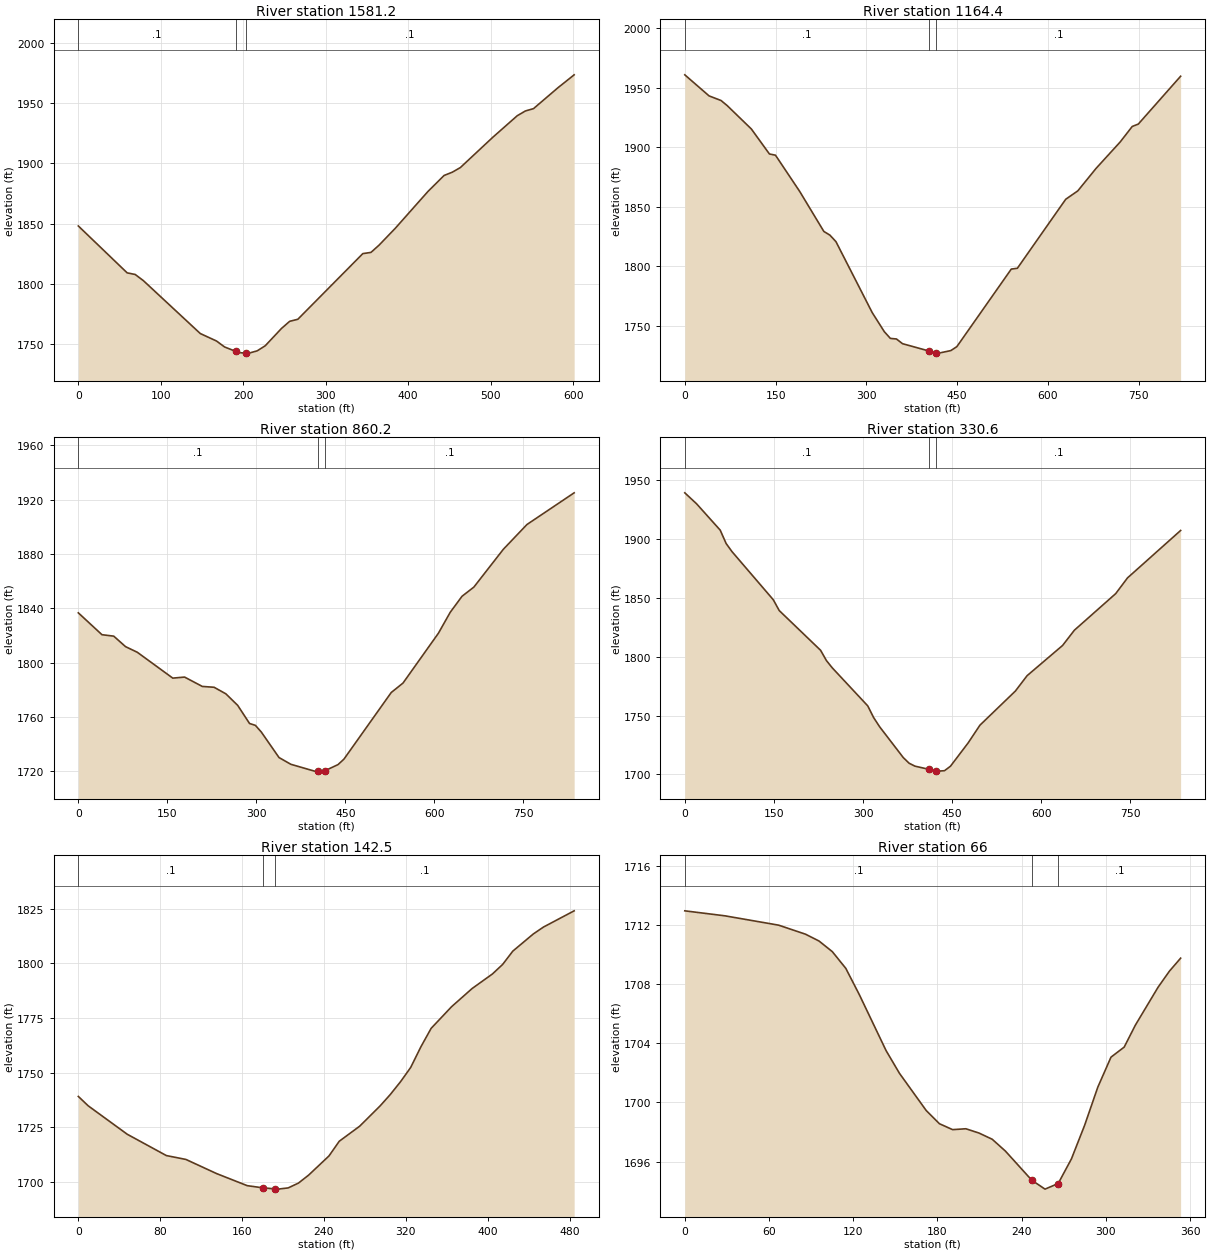
Type RM Length L Ch R = 1 ,1581.2  ,419.8,416.8,413.8
XS GIS Cut Line= 2
      1983741.48      121009.591     1983850.525      121600.953
#Sta/Elev= 30
       0 1848.18    59.2 1809.31      69 1807.95    78.9 1802.84   147.9 1758.99
   167.6 1752.78   177.4 1747.84   191.1 1744.14   197.2 1743.01   203.1 1742.85
     207 1742.75   216.9 1744.64   226.7 1748.87   246.4 1763.22   256.3 1769.12
   266.2 1770.82     345 1825.25   354.9 1826.27   364.7 1832.27   384.5 1846.35
   423.9 1876.72   443.6 1890.07   453.5 1892.76   463.3  1896.6   502.8 1921.81
   532.3  1939.6   542.2 1943.54     552 1945.46   581.6 1962.76   601.3  1973.5
#Mann= 3 , 0 , 0
       0      .1       0   191.1    .045       0   203.1      .1       0
Bank Sta=191.1,203.1
XS Rating Curve= 0 ,0
Exp/Cntr=0.3,0.1

Type RM Length L Ch R = 1 ,1164.4  ,311.6,304.2,296.8
XS GIS Cut Line= 3
     1983249.329      120938.579     1983379.977      121326.679
     1983510.625      121714.779
#Sta/Elev= 30
       0 1960.65      40 1943.02    59.9  1939.1    69.9 1934.92   109.9 1915.26
   139.8 1894.29   149.8 1893.26   189.8 1862.89   229.7 1829.33   239.7 1826.25
   249.7 1820.76   309.6 1761.28   329.6 1745.28   339.6 1739.65   349.6 1739.18
   359.6 1735.24   403.5 1729.07   415.5 1727.66   419.5 1727.32   439.5 1729.46
   449.4 1732.77   539.3 1797.79   549.3 1798.44   629.2 1856.31   649.2 1863.37
   679.2 1882.12   719.1 1904.32   739.1 1917.37   749.1 1919.35     819 1959.47
#Mann= 3 , 0 , 0
       0      .1       0   403.5    .045       0   415.5      .1       0
Bank Sta=403.5,415.5
XS Rating Curve= 0 ,0
Exp/Cntr=0.3,0.1

Type RM Length L Ch R = 1 ,860.2   ,548.7,529.6,510.4
XS GIS Cut Line= 2
     1982848.758      121133.894     1983370.853      121786.628
#Sta/Elev= 30
       0 1836.58    39.8  1820.5    59.7 1819.43    79.6  1811.7    99.5 1807.54
   159.2 1788.53   179.1 1789.29     209 1782.41   228.9 1781.79   248.8 1776.93
   268.7 1768.44   288.6 1755.14   298.5 1753.74   308.5 1748.81   338.3 1730.06
   358.2  1725.1     398 1720.06   404.2 1720.08   416.2 1720.45   437.8 1724.87
   447.8 1728.92   527.4 1777.91   547.3 1784.89     607 1821.59   626.9 1836.99
   646.8 1848.79   666.7 1855.52   716.4 1883.36   756.2  1901.6   835.8 1924.94
#Mann= 3 , 0 , 0
       0      .1       0   404.2    .045       0   416.2      .1       0
Bank Sta=404.2,416.2
XS Rating Curve= 0 ,0
Exp/Cntr=0.3,0.1

Type RM Length L Ch R = 1 ,330.6   ,186,188,189.9
XS GIS Cut Line= 2
      1982498.45      121898.546     1983333.084      121888.783
#Sta/Elev= 30
       0 1939.33    19.9 1929.98    59.6 1907.64    69.6 1896.26    79.5 1889.34
     149 1848.46     159 1839.28   228.6 1805.54   238.5 1796.74   248.4 1790.54
     308  1758.3     318 1748.29   327.9 1740.61   367.7 1714.43   377.6 1709.58
   387.5 1707.08   411.2 1704.37   423.2 1703.18   427.3 1702.86   437.2 1703.22
   447.2 1707.02     477 1726.83   496.8 1741.86   556.5 1770.89   576.3 1783.98
     636 1809.64   655.8 1822.57   725.4 1853.68   745.3 1867.05   834.7 1907.34
#Mann= 3 , 0 , 0
       0      .1       0   411.2    .045       0   423.2      .1       0
Bank Sta=411.2,423.2
XS Rating Curve= 0 ,0
Exp/Cntr=0.3,0.1

Type RM Length L Ch R = 1 ,142.5   ,71.2,76.5,81.8
XS GIS Cut Line= 4
     1982735.756      122050.158       1982838.4      122072.758
      1982977.77      122084.058     1983208.484      122020.024
#Sta/Elev= 30
       0 1739.04     9.6 1734.75    47.8 1721.69      86 1711.92   105.1 1710.14
   135.1 1703.65     165 1698.12   180.3 1697.12   192.3 1696.63     195 1696.53
     205 1697.09     215 1699.28     225 1702.96   244.9 1711.76   254.9 1718.48
   274.9  1725.4   294.8 1734.68   304.8 1739.93   314.8  1745.8   324.7 1752.32
   334.7 1761.82   344.7 1770.27   364.6 1780.16   384.6 1788.48   404.6 1795.21
   414.5 1799.55   424.5 1805.68   444.5 1813.54   454.4  1816.7   484.4 1824.15
#Mann= 3 , 0 , 0
       0      .1       0   180.3    .045       0   192.3      .1       0
Bank Sta=180.3,192.3
XS Rating Curve= 0 ,0
Exp/Cntr=0.3,0.1

Type RM Length L Ch R = 1 ,66      ,93.6,66,38.4
XS GIS Cut Line= 4
     1982691.496      122121.726     1982861.983       122144.85
     1983002.254      122158.452     1983039.921      122144.327
#Sta/Elev= 29
       0 1712.95    28.7 1712.61    66.9 1711.98      86 1711.37    95.6 1710.91
   105.1 1710.19   114.7 1709.06   124.3 1707.29   143.4  1703.5   152.9 1701.97
     172 1699.45   181.4 1698.56   190.8 1698.16   200.2 1698.22   209.6 1697.93
     219 1697.51   228.4 1696.71   247.2 1694.74   256.6 1694.14     266 1694.52
   275.4 1696.18   284.8 1698.45   294.2 1701.03   303.6 1703.06     313 1703.74
     321 1705.23   337.1 1707.78   345.2 1708.87   353.2 1709.75
#Mann= 3 , 0 , 0
       0      .1       0   247.2    .045       0     266      .1       0
Bank Sta=247.2,266
XS Rating Curve= 0 ,0
Exp/Cntr=0.3,0.1

Chan Stop Cuts=-1
Use User Specified Reach Order=0
Composite Channel Slope=5